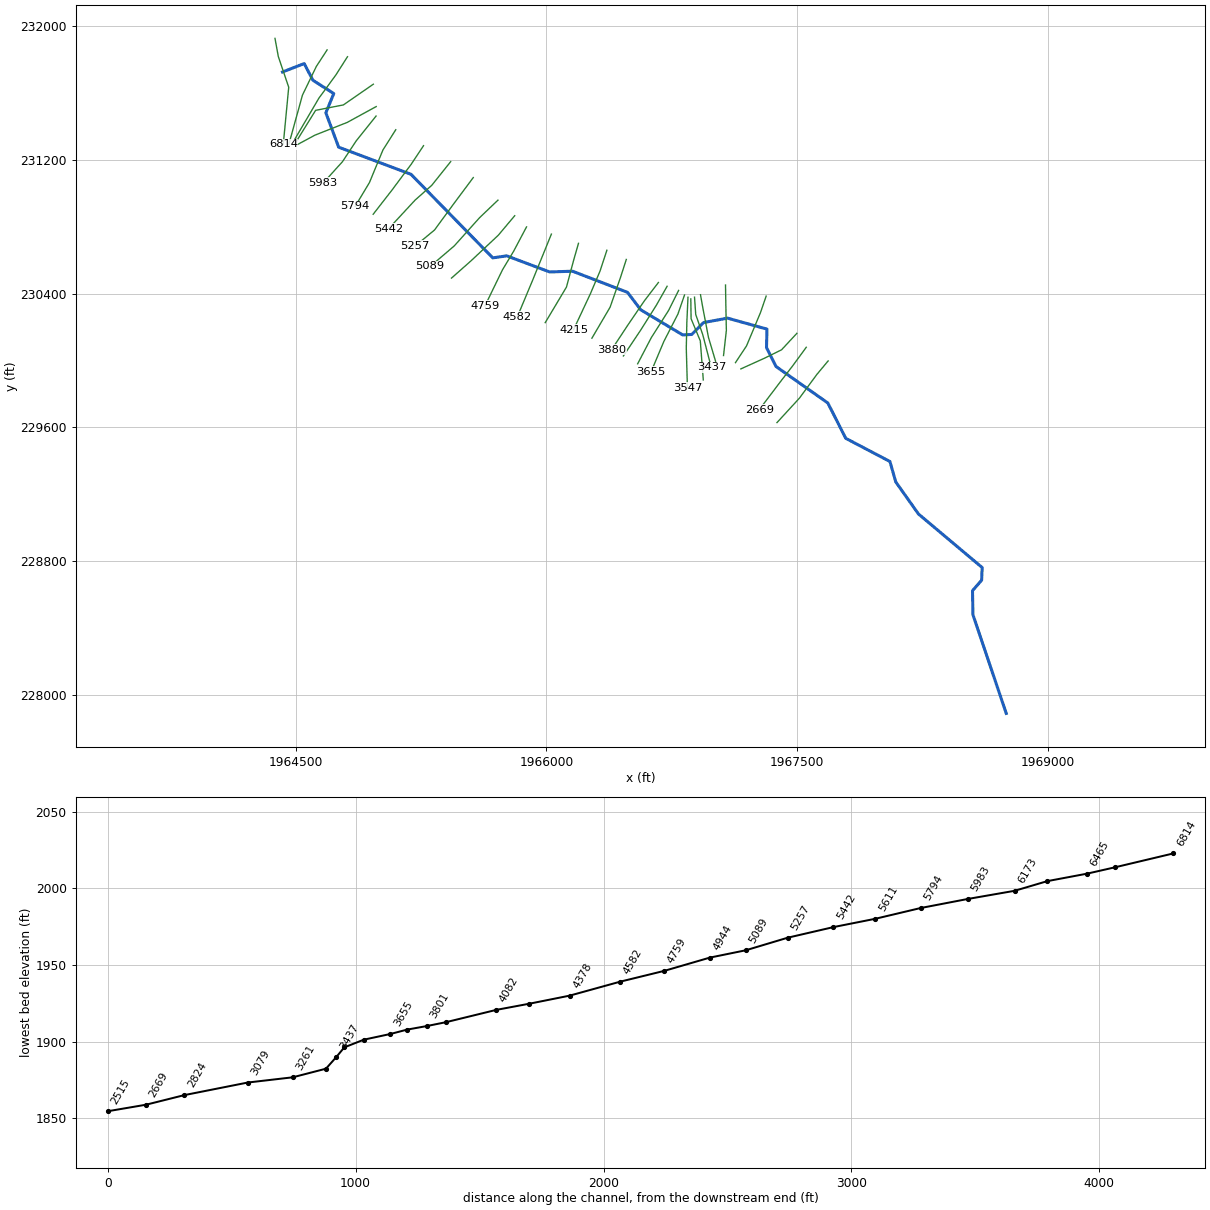
--- WHOAKBR.prj (project) ---

Proj Title=WHOAKBR
Current Plan=p01
Default Exp/Contr=0,0
English Units
Geom File=g01
Flow File=f01
Plan File=p01
BEGIN DESCRIPTION:
Stream Name: White Oak Branch
Flood Zone: Approximate
Summers County, West Virginia
HEC-RAS Version: 5.0.7
Hydrology Method:
Regression.
Model Notes:
END DESCRIPTION:
DSS Export Rating Curves= 0
DSS Export Rating Curve Sorted= 0
DSS Export Volume Flow Curves= 0
DXF OffsetX= 0
DXF OffsetY= 0
DXF ScaleX= 0
DXF ScaleY= 0

--- WHOAKBR.p01 (plan) ---

Plan Title=Floodplain
Program Version=5.07
Short Identifier=Floodplain
Geom File=g01
Flow File=f01
Subcritical Flow
K Sum by GR= 0
Std Step Tol= 0.01
Critical Tol= 0.01
Num of Std Step Trials= 20
Max Error Tol= 0.3
Flow Tol Ratio= 0.001
Split Flow NTrial= 30
Split Flow Tol= 0.02
Split Flow Ratio= 0.02
Log Output Level= 0
Friction Slope Method= 1
Unsteady Friction Slope Method= 2
Unsteady Bridges Friction Slope Method= 1
Parabolic Critical Depth
Global Vel Dist= 0 , 0 , 0
Global Log Level= 0
CheckData=True
Encroach Param=-1 ,0,0, 0
Mapping Interval=1HOUR
Computation Time Step Use Courant=        0
Computation Time Step Use Time Series=    0
Computation Time Step Count To Double=0
Computation Time Step Max Doubling=0
Computation Time Step Max Halving=0
Computation Time Step Residence Courant=0
Run HTab= 0
Run UNet= 0
Run Sediment= 0
Run PostProcess= 0
Run WQNet= 0
Run RASMapper= 0
UNET Theta= 0
UNET Theta Warmup= 0
UNET ZTol= 0
UNET ZSATol= 0
UNET MxIter= 0
UNET Max Iter WO Improvement= 0
UNET MaxInSteps= 0
UNET DtIC= 0
UNET DtMin= 0
UNET MaxCRTS= 0
UNET WFStab= 0
UNET SFStab= 0
UNET WFX= 1
UNET SFX= 1
UNET 1D Methodology=Finite Difference
UNET DSS MLevel= 1
UNET Pardiso=0
UNET DZMax Abort= 0
UNET Use Existing IB Tables= 0
UNET Froude Reduction=False
UNET Froude Limit= 0
UNET Froude Power= 0
UNET D1 Cores= 0
UNET D2 Coriolis=0
UNET D2 Cores= 0
UNET D2 Theta= 1
UNET D2 Theta Warmup= 1
UNET D2 Z Tol= 0.01
UNET D2 Volume Tol= 0.01
UNET D2 Max Iterations= 20
UNET D2 Equation= 0
UNET D2 RampUpFraction=0.1
UNET D2 TimeSlices= 1
UNET D2 BCVolumeCheck=0
UNET D1D2 MaxIter= 0
UNET D1D2 ZTol=0.01
UNET D1D2 QTol=0.1
UNET D1D2 MinQTol=1
Write IC File= 0
Write IC File at Fixed DateTime=0
Write IC File at Sim End=0
Echo Input=False
Echo Parameters=False
Echo Output=False
Write Detailed= 0
HDF Write Warmup=0
HDF Write Time Slices=0
HDF Flush=0
HDF Face Node Velocities=0
HDF Compression= 1
HDF Chunk Size= 1
HDF Spatial Parts= 1
HDF Use Max Rows=0
HDF Fixed Rows= 1
Calibration Method= 0
Calibration Iterations= 20
Calibration Max Change=0.05
Calibration Tolerance=0.2
Calibration Maximum=1.5
Calibration Minimum=0.5
Calibration Optimization Method= 1
WQ AD Non Conservative
WQ ULTIMATE=-1
WQ Max Comp Step=1HOUR
WQ Output Interval=15MIN
WQ Output Selected Increments= 0
WQ Output face flow=0
WQ Output face velocity=0
WQ Output face area=0
WQ Output face dispersion=0
WQ Output cell volume=0
WQ Output cell surface area=0
WQ Output cell continuity=0
WQ Output cumulative cell continuity=0
WQ Output face conc=0
WQ Output face dconc_dx=0
WQ Output face courant=0
WQ Output face peclet=0
WQ Output face adv mass=0
WQ Output face disp mass=0
WQ Output cell mass=0
WQ Output cell source sink temp=0
WQ Output nsm pathways=0
WQ Output nsm derived pathways=0
WQ Output MaxMinRange=-1
WQ Daily Max Min Mean=-1
WQ Daily Range=0
WQ Daily Time=0
WQ Create Restart=0
WQ Fixed Restart=0
WQ System Summary=0
WQ Write To DSS=0
WQ Use Fixed Temperature=0
Sorting and Armoring Iterations= 10
XS Update Threshold= 0.02
Bed Roughness Predictor= 0
Hydraulics Update Threshold= 0.02
Energy Slope Method= 1
Volume Change Method= 1
Sediment Retention Method= 0
XS Weighting Method= 0
Number of US Weighted Cross Sections= 1
Number of DS Weighted Cross Sections= 1
Upstream XS Weight=0
Main XS Weight=1
Downstream XS Weight=0
Number of DS XS's Weighted with US Boundary= 1
Upstream Boundary Weight= 1
Weight of XSs Associated with US Boundary= 0
Number of US XS's Weighted with DS Boundary= 1
Downstream Boundary Weight= 0.5
Weight of XSs Associated with DS Boundary= 0.5
Percentile Method= 0
Sediment Output Level= 3
Mass or Volume Output= 0
Output Increment Type= 1
Profile and TS Output Increment= 1
XS Output Flag= 0
XS Output Increment= 10
Write Gradation File= 0
Read Gradation Hotstart= 0
Write HDF5 File= 1
Write Binary Output= 1
Write DSS Sediment File= 0
SV Curve= 0
Specific Gage Flag= 0

--- WHOAKBR.f01 (steady flow) ---

Flow Title=Flows
Program Version=5.07
Number of Profiles= 6
Profile Names=01pct,10pct,04pct,02pct,0_2pct,01plus
River Rch & RM=WHOAKBR,Main            ,6814
     572     302     402     484     799     846
River Rch & RM=WHOAKBR,Main            ,3880
     643     341     453     545     896     951
Boundary for River Rch & Prof#=WHOAKBR,Main            , 1
Up Type= 0
Dn Type= 3
Dn Slope=0.02362
Boundary for River Rch & Prof#=WHOAKBR,Main            , 2
Up Type= 0
Dn Type= 3
Dn Slope=0.02362
Boundary for River Rch & Prof#=WHOAKBR,Main            , 3
Up Type= 0
Dn Type= 3
Dn Slope=0.02362
Boundary for River Rch & Prof#=WHOAKBR,Main            , 4
Up Type= 0
Dn Type= 3
Dn Slope=0.02362
Boundary for River Rch & Prof#=WHOAKBR,Main            , 5
Up Type= 0
Dn Type= 3
Dn Slope=0.02362
Boundary for River Rch & Prof#=WHOAKBR,Main            , 6
Up Type= 0
Dn Type= 3
Dn Slope=0.02362
DSS Import GetInterval= 0
DSS Import GetPeak= 0
DSS Import FillOption= 0

--- WHOAKBR.g01 (geometry) ---

Geom Title=Geometry
Program Version=5.07

River Reach=WHOAKBR         ,Main
Reach XY= 30
     1964420.274      231726.371     1964549.973      231776.809
     1964602.377      231676.587      1964727.02      231597.348
     1964679.672      231482.039     1964756.313      231276.354
     1965189.342      231113.9621965678.54666545230613.936546023
1965761.93506738230626.079940153      1966019.24      230529.603
     1966155.489      230534.188      1966484.85      230407.631
     1966564.237      230302.957      1966815.12      230152.952
     1966869.488      230155.572     1966940.233      230226.972
     1967083.688      230253.174     1967319.505      230187.669
     1967316.838      230076.598     1967373.874      229963.643
      1967683.71      229745.514     1967791.137      229533.934
     1968055.336      229395.392     1968090.275      229273.095
     1968226.087      229081.297     1968607.463       228760.64
     1968604.281      228685.108      1968549.68      228622.111
     1968552.118      228478.674     1968751.453       227887.92

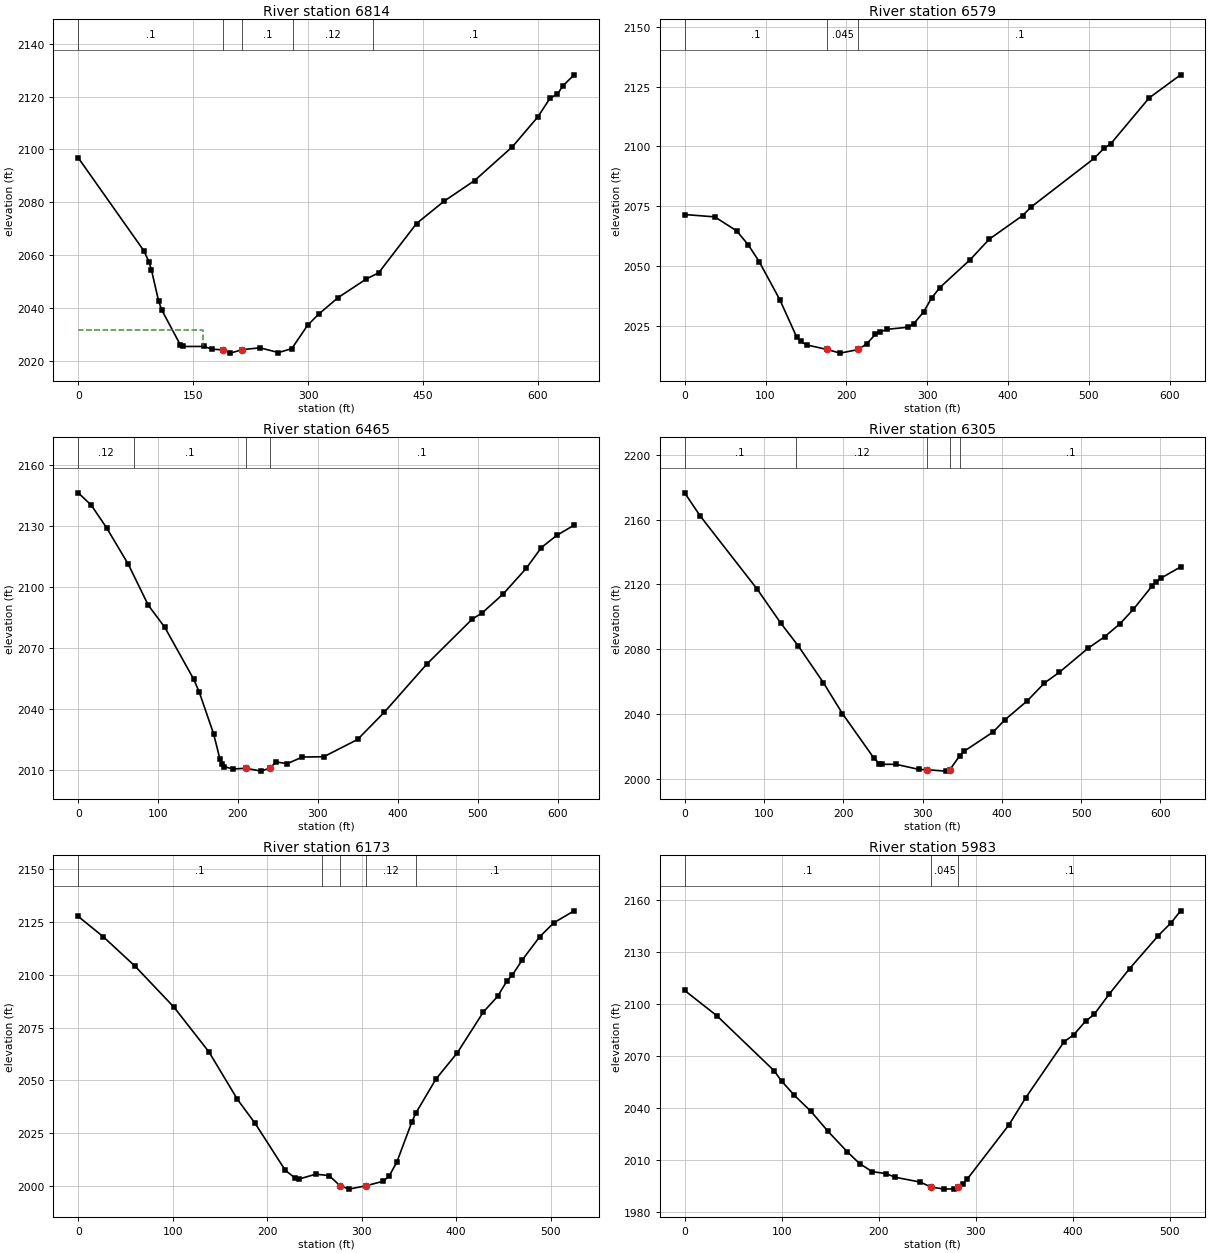
Type RM Length L Ch R = 1 ,6814    ,244.7,235,214
XS GIS Cut Line= 4
1964375.17464276231927.7882422481964395.07872486231819.081332367
1964457.43043614231635.1611679861964424.88321986231294.319486405
#Sta/Elev= 30
       0 2096.82    85.6 2061.63    92.2 2057.51    95.6 2054.32   104.8 2042.68
   108.9 2039.25   133.1 2026.06   136.6 2025.38   164.3 2025.39   174.7 2024.34
  188.632024.118   198.5 2022.86     214 2024.16     237 2024.88   261.3 2023.07
   278.7 2024.57   299.2 2033.38   313.7 2037.61   339.2  2043.9   375.5 2050.85
     392 2053.26   441.4 2071.91   477.6 2080.42   517.2 2088.19   566.6    2101
   599.6 2112.24     616  2119.5   625.1 2120.84   632.5 2124.07   647.1 2128.21
#Mann= 5 ,-1 , 0
       0      .1       0  188.63    .045       0     214      .1       0
  280.51     .12       0  384.72      .1       0
#XS Ineff= 2 , 0
          162.46 2031.66
Permanent Ineff=
       F       F
Bank Sta=188.63,214
XS Rating Curve= 0 ,0
Exp/Cntr(USF)=0,0
Exp/Cntr=0.3,0.1

Type RM Length L Ch R = 1 ,6579    ,119.7,113.8,107.1
XS GIS Cut Line= 4
1964687.06912877231858.4712352291964622.87878556231759.925497053
1964539.70256618231588.1485222511964458.33452548231294.319486405
#Sta/Elev= 30
       0 2071.63    37.3 2070.64    64.2 2064.84    78.6    2059    92.1 2052.03
   117.6 2036.15   138.4 2020.64   143.3 2018.74   150.7 2017.27  176.09 2015.35
   192.4 2013.83  214.85 2015.35   225.1  2017.7     236 2021.72   241.5 2022.65
   250.6 2023.76   276.1 2024.63   283.3 2026.06   295.6 2031.07   305.3 2036.74
   315.7 2041.19   353.2 2052.83   376.8 2061.38   417.9 2071.18   428.6 2074.79
   506.4 2095.02   518.4 2099.18   526.8 2101.05   574.5 2120.25   613.4 2129.88
#Mann= 3 ,-1 , 0
       0      .1       0  176.09    .045       0  214.85      .1       0
Bank Sta=176.09,214.85
XS Rating Curve= 0 ,0
Exp/Cntr(USF)=0,0
Exp/Cntr=0.3,0.1

Type RM Length L Ch R = 1 ,6465    ,177.4,160,142.8
XS GIS Cut Line= 4
1964809.12118982231817.7872148821964739.50631056231708.392404613
1964638.24830436 231570.066735431964476.41631231231294.319486405
#Sta/Elev= 30
       0 2146.46    16.3 2140.41    35.5 2129.28    62.7 2111.33    87.6 2091.28
   108.4 2080.32   144.5 2054.87   151.5 2048.51   169.5 2027.96   177.3 2015.72
   179.7  2013.2     182  2011.9   193.6 2010.72   210.1 2011.03     229 2009.64
  239.852011.158   247.7 2014.14   261.8 2013.33   280.6 2016.58   307.3  2016.7
   349.7  2025.2   383.3 2038.65     436 2062.11   493.5  2084.5   505.1 2087.24
   531.9  2096.7   560.7 2109.29   579.8 2119.56     599 2125.54   620.8 2130.57
#Mann= 4 ,-1 , 0
       0     .12       0      70      .1       0   210.1    .045       0
  239.85      .1       0
Bank Sta=210.1,239.85
XS Rating Curve= 0 ,0
Exp/Cntr(USF)=0,0
Exp/Cntr=0.3,0.1

Type RM Length L Ch R = 1 ,6305    ,125.8,131.7,133.4
XS GIS Cut Line= 4
1964963.72046714231653.2429548081964784.71077761231529.382715082
1964618.35833885231496.8354988031964492.68992044231294.319486405
#Sta/Elev= 30
       0 2176.47    19.4 2162.31    91.6 2116.94   120.9  2096.3   143.1 2082.14
     175 2059.32   198.9 2040.32   238.7 2012.78   245.4 2009.47   248.8 2009.01
   266.7 2008.97   295.6 2005.81   305.8 2005.65     329 2004.78   334.4  2005.6
   346.8 2014.21   352.4 2017.03   389.3 2029.02   403.6 2036.33   432.2 2048.18
   453.6 2059.08   472.7 2065.82   508.4 2080.45   529.9 2087.78     549 2095.68
     566 2104.67   589.1 2118.76   594.2 2121.18   600.7 2123.84   625.5 2130.77
#Mann= 5 ,-1 , 0
       0      .1       0     140     .12       0   305.8    .045       0
   334.4     .12       0  347.68      .1       0
Bank Sta=305.8,334.4
XS Rating Curve= 0 ,0
Exp/Cntr(USF)=0,0
Exp/Cntr=0.3,0.1

Type RM Length L Ch R = 1 ,6173    ,175.1,190.2,201.2
XS GIS Cut Line= 4
1964980.89816462 231519.437732331964807.31301114231424.508351518
1964614.74198149231348.5648468691964508.96352858231291.607218382
#Sta/Elev= 30
       0 2127.61    26.5 2117.99    60.2 2104.03   101.3 2084.67   138.5 2063.38
   168.6 2040.94   187.3  2029.6   219.2 2007.38   229.3 2003.86   233.8 2003.27
   251.4 2005.54   265.5 2004.91  277.162000.103   286.7 1998.48  304.912000.103
   322.9 2002.21     329 2004.61   337.2 2011.17   353.2  2030.3   357.2 2034.31
   378.5 2050.47   401.3 2063.04     429 2082.41   443.9 2089.71     454 2097.15
   459.6 2099.84     470 2106.97   488.6    2118   503.5  2124.6     525 2130.25
#Mann= 5 ,-1 , 0
       0      .1       0  257.85     .12       0  277.16    .045       0
  304.91     .12       0  357.85      .1       0
Bank Sta=277.16,304.91
XS Rating Curve= 0 ,0
Exp/Cntr(USF)=0,0
Exp/Cntr=0.3,0.1

Type RM Length L Ch R = 1 ,5983    ,182.5,189.2,192.8
XS GIS Cut Line= 4
1964980.22846881 231462.775266071964861.17143624231313.953975359
1964779.31972635231189.9362331011964663.98322605231062.197958574
#Sta/Elev= 30
       0 2107.94    33.3 2093.27    92.1  2061.6    99.9 2055.59   113.1 2047.32
   130.3 2037.99   147.7 2026.56   167.7 2014.66   180.3 2007.91   193.3 2003.24
   207.5 2002.08     217 1999.99   243.1 1997.17  253.56 1994.39   267.5 1993.12
   277.5 1993.31  282.051994.392   287.1 1996.34   291.1 1998.76   334.3 2030.26
   351.7 2046.03   391.2 2078.33   401.1 2082.31   413.3  2090.2   422.1 2094.07
   437.7 2105.85   458.6  2120.5   488.4  2139.7   501.7 2147.18   511.3 2153.97
#Mann= 3 ,-1 , 0
       0      .1       0  253.56    .045       0  282.05      .1       0
Bank Sta=253.56,282.05
XS Rating Curve= 0 ,0
Exp/Cntr(USF)=0,0
Exp/Cntr=0.3,0.1

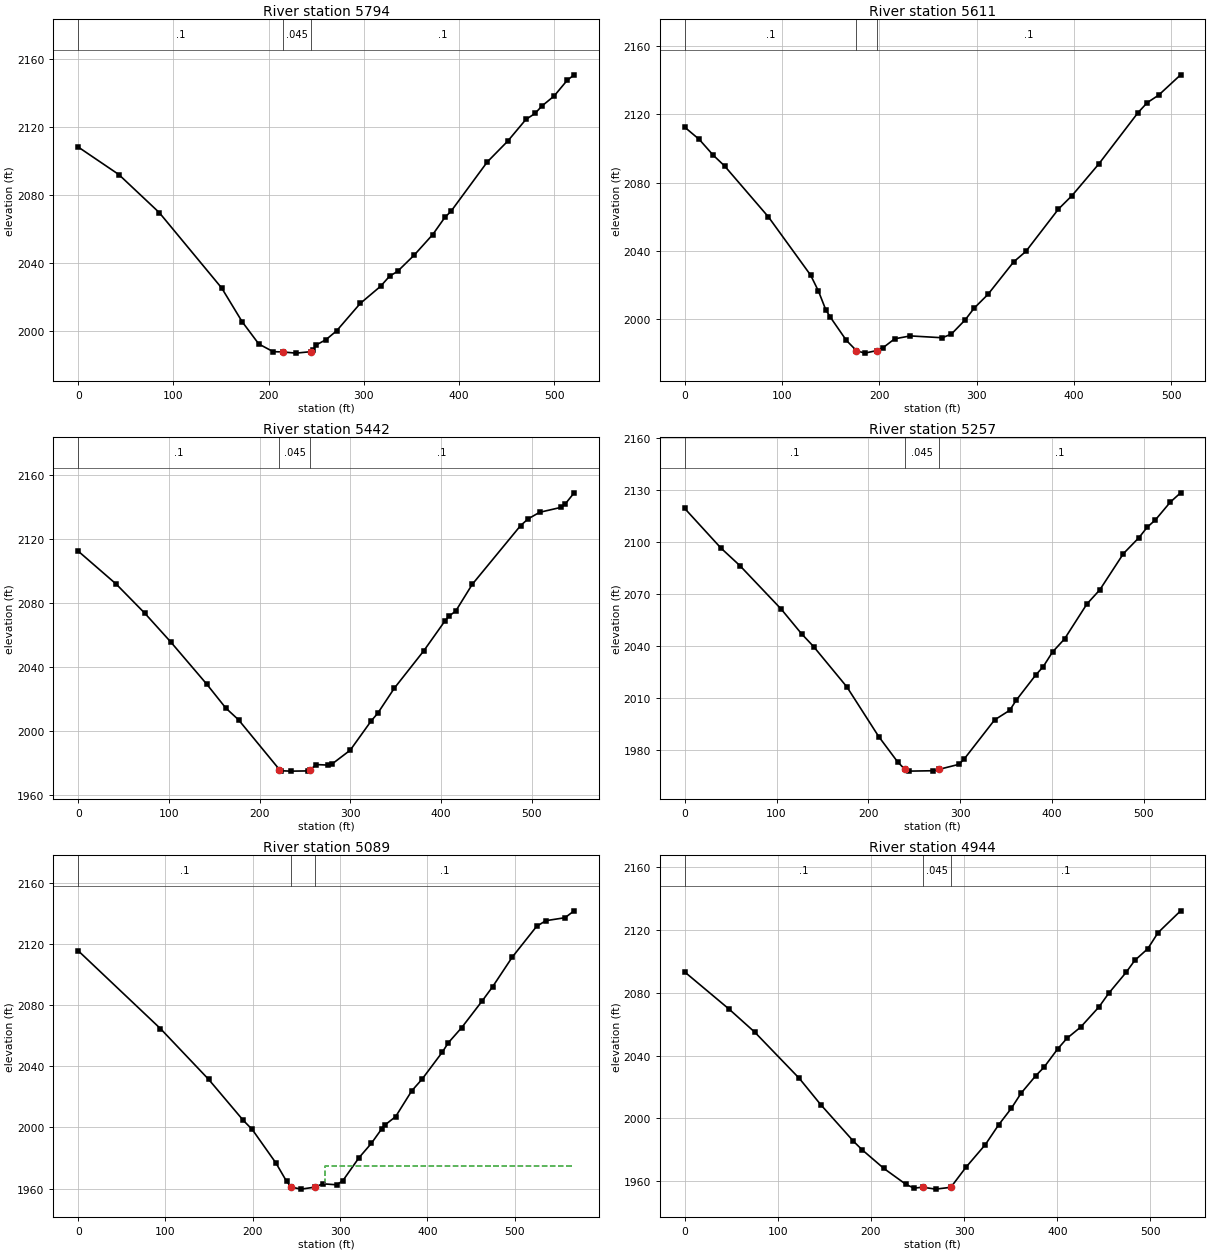
Type RM Length L Ch R = 1 ,5794    ,186.7,183,178
XS GIS Cut Line= 4
1965098.04532396231380.9235561791965021.15432376231259.386168766
1964940.54279129 231064.678313421964854.97054913230922.057909822
#Sta/Elev= 30
       0 2108.47    42.6 2092.31    85.1 2069.92   150.7 2025.54   172.2  2005.7
   189.7  1992.6   204.8 1988.09   214.6 1987.94   228.8 1987.24   244.2 1988.09
   246.5 1988.83   250.1 1992.09   260.1 1995.11   271.4 2000.35   296.2 2016.45
   317.6 2026.57     327 2032.48   335.4 2035.33   352.8 2044.84   372.4 2057.01
   385.1 2067.08   391.5 2070.62   429.7 2099.73   451.1 2111.92   470.2 2124.68
   479.8 2128.21   486.9 2132.53   499.9  2138.5   513.6 2147.73   520.9 2150.94
#Mann= 3 ,-1 , 0
       0      .1       0   214.6    .045       0   244.2      .1       0
Bank Sta=214.6,244.2
XS Rating Curve= 0 ,0
Exp/Cntr(USF)=0,0
Exp/Cntr=0.3,0.1

Type RM Length L Ch R = 1 ,5611    ,171.7,168.5,163.8
XS GIS Cut Line= 4
1965264.22909858 231285.429894641965191.05863065 231175.05410403
1965075.72213035231020.031926207 1964962.8659849230874.931167764
#Sta/Elev= 30
       0 2112.52      15 2105.33    29.2 2096.18      41  2089.8    86.1 2059.92
   129.4 2025.87   137.4 2016.58     145 2005.54   149.7 2001.22   166.1 1987.68
  176.451981.682   184.9 1980.22  197.171981.682   203.6  1983.3   215.7 1988.59
   231.8  1990.3   264.6 1989.22     274 1991.37   288.1 1999.65   297.4 2006.56
   311.5 2014.57     338 2033.66   350.5 2039.75     384 2064.57     398 2072.49
   425.3 2090.87   465.8 2121.06   475.2 2126.87   486.9 2131.26   509.5 2143.16
#Mann= 3 ,-1 , 0
       0      .1       0  176.45    .045       0  197.17      .1       0
Bank Sta=176.45,197.17
XS Rating Curve= 0 ,0
Exp/Cntr(USF)=0,0
Exp/Cntr=0.3,0.1

Type RM Length L Ch R = 1 ,5442    ,179.5,184.8,191.4
XS GIS Cut Line= 4
1965426.69234094231189.9362331011965313.83619549231048.556006926
1965213.38182426  230959.26323251965055.87929159230789.358925606
#Sta/Elev= 30
       0 2112.53    41.9  2091.9    73.5 2073.62   102.1 2055.64   141.8 2029.24
   162.8 2014.28   176.8 2006.96  221.961975.774   223.7 1975.02   234.9 1974.81
   253.5 1974.94  255.891975.773   262.8 1978.92   275.6 1978.58     280 1979.29
     300 1987.91   323.2 2006.29   330.2 2010.91   348.7 2026.76   381.2 2050.17
   404.5 2068.83   409.1  2071.9   416.4 2075.03   434.6 2091.74     488 2128.58
   496.3 2132.76   508.9 2136.84   532.1 2139.88   537.1 2142.02     547 2149.04
#Mann= 3 ,-1 , 0
       0      .1       0  221.96    .045       0  255.89      .1       0
Bank Sta=221.96,255.89
XS Rating Curve= 0 ,0
Exp/Cntr(USF)=0,0
Exp/Cntr=0.3,0.1

Type RM Length L Ch R = 1 ,5257    ,169.4,168.7,163.1
XS GIS Cut Line= 4
   1965561.87168231094.4425715621965452.73606682230948.101635697
1965329.95850198230780.6776836471965214.62200168230685.184022108
#Sta/Elev= 30
       0 2119.16    39.5 2096.31      60 2086.27     105 2061.22   127.2 2046.99
   140.3 2039.63   176.6 2016.36   211.2 1987.81   231.7 1973.29  239.671968.923
   243.8 1967.88   270.8 1968.11  277.051968.921   298.6 1971.79   304.5    1975
   337.4 1997.39   353.8 2002.88   360.8 2008.61   382.1 2023.19   390.3 2028.02
   400.5 2036.51   413.5 2043.98   437.9 2064.14   451.9 2072.26   477.7 2093.18
   494.5  2102.3   503.4 2108.25   512.5 2112.59   528.8 2122.86   539.9 2128.14
#Mann= 3 ,-1 , 0
       0      .1       0  239.67    .045       0  277.05      .1       0
Bank Sta=239.67,277.05
XS Rating Curve= 0 ,0
Exp/Cntr(USF)=0,0
Exp/Cntr=0.3,0.1

Type RM Length L Ch R = 1 ,5089    ,146.6,145.1,142.7
XS GIS Cut Line= 4
1965709.45279329  230959.2632325 1965600.3171801230855.088329003
1965447.77535713230685.1840221081965303.91477611230562.406457272
#Sta/Elev= 30
       0  2115.5    94.2 2064.62   149.4 2031.47   189.2 2004.61   199.4 1998.69
   226.6 1976.73   238.7 1964.86  244.121961.016   255.4  1959.7  271.461961.017
     280  1963.2   296.3 1962.52   303.3 1965.28   321.8 1980.27   335.8 1989.53
   347.9 1999.18     352 2001.88   363.7 2007.06   382.2 2023.94   393.9 2031.48
   417.2 2049.21   424.1 2055.36   439.4 2065.25   462.9  2082.7   474.8 2091.93
   497.4 2111.36   525.3 2131.45   535.8 2135.15   557.8  2137.1   568.3  2141.6
#Mann= 3 ,-1 , 0
       0      .1       0  244.12    .045       0  271.46      .1       0
#XS Ineff= 2 , 0
                          282.81         1974.72
Permanent Ineff=
       F       F
Bank Sta=244.12,271.46
XS Rating Curve= 0 ,0
Exp/Cntr(USF)=0,0
Exp/Cntr=0.3,0.1

Type RM Length L Ch R = 1 ,4944    ,155.3,184.2,168.6
XS GIS Cut Line= 4
1965809.90716452230866.2499258061965711.93314814230749.673248083
1965549.46990578230597.1314251051965431.65305063230492.956521608
#Sta/Elev= 30
       0  2093.4    47.6 2069.73    75.3 2054.96   123.1  2025.5   146.1 2008.74
   181.2 1985.43   190.5 1979.99   213.7 1968.16   237.4    1958   246.2 1955.53
   255.5 1956.14   269.4 1954.91   285.7 1956.06   301.9  1968.8   322.8 1983.32
   337.1 1995.95   350.7 2006.46   361.1 2016.05   376.9 2027.24   385.6 2032.51
   400.3  2044.2   410.2 2050.99   425.1 2058.23   444.8 2071.12   455.2 2079.78
   473.8 2093.06   483.1 2100.71   497.1 2108.18   508.2 2118.47   532.4 2132.37
#Mann= 3 ,-1 , 0
       0      .1       0   255.5    .045       0   285.7      .1       0
Bank Sta=255.5,285.7
XS Rating Curve= 0 ,0
Exp/Cntr(USF)=0,0
Exp/Cntr=0.3,0.1

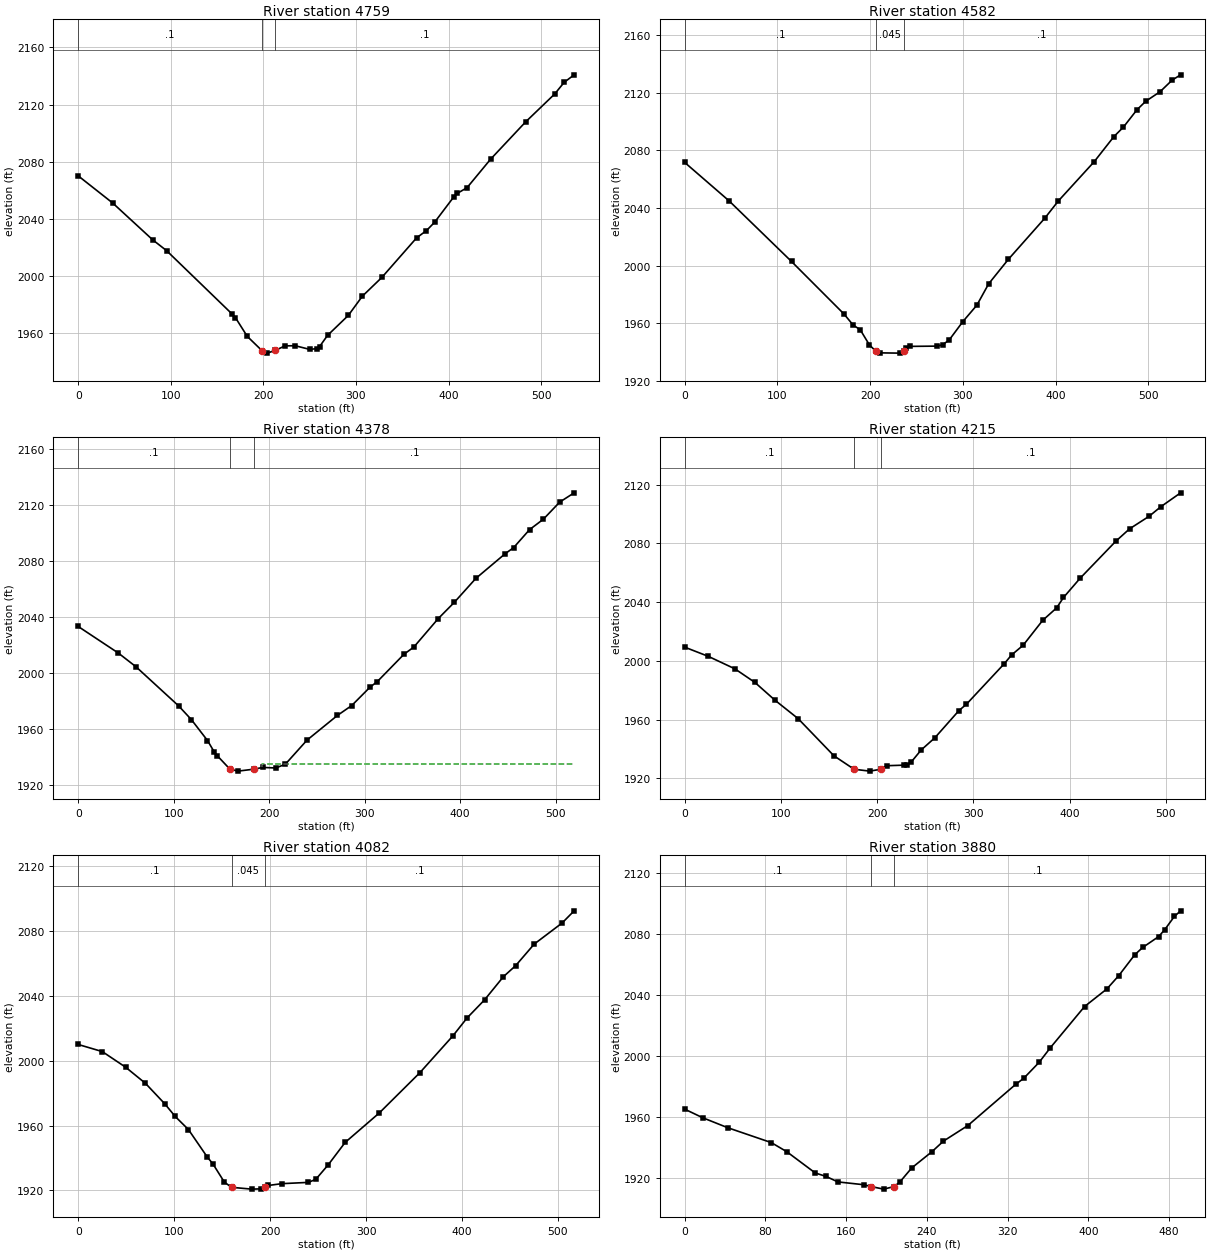
Type RM Length L Ch R = 1 ,4759    ,177.7,177.6,199.4
XS GIS Cut Line= 4
1965880.59727761230799.2803449861965803.70627741230654.179586544
1965736.73669659230542.5636185111965631.32161567230325.532569558
#Sta/Elev= 30
       0  2070.2    37.3 2051.18    80.5 2025.44    95.4 2017.94     166 1973.73
   169.8  1971.1   182.6 1957.97   198.4 1948.05   204.2 1946.25   212.9 1948.19
   223.4 1951.33   234.4 1951.42   250.1 1948.86   257.8  1949.4   260.7 1950.82
   269.3 1958.63   291.8 1972.65   306.9 1986.05     328 1999.19   365.5 2026.84
   376.2 2031.95     385 2037.78   405.4 2055.25   409.5 2057.97     420 2061.93
   445.5 2081.89   483.2 2107.87   514.8 2127.52   524.9 2135.59   535.7 2140.84
#Mann= 3 ,-1 , 0
       0      .1       0   198.4    .045       0   212.9      .1       0
Bank Sta=198.4,212.9
XS Rating Curve= 0 ,0
Exp/Cntr(USF)=0,0
Exp/Cntr=0.3,0.1

Type RM Length L Ch R = 1 ,4582    ,203.3,204.3,209.6
XS GIS Cut Line= 4
1966029.29608166230756.0884868491965969.58383539230609.104496024
1965915.99592207230477.4313375771965825.66201104230261.548601052
#Sta/Elev= 30
       0 2071.56    47.9 2044.87   115.2 2002.82   171.7 1966.42   181.7 1958.68
   189.3 1955.45   199.3 1944.83  206.451940.386   210.8  1939.4     232 1939.22
  236.21 1940.39   239.1 1942.73   242.7  1943.9   272.4 1944.09   278.1 1945.03
   285.2 1948.31     300 1961.12   315.1  1972.5   327.8 1987.32   349.1 2004.35
   388.3 2032.83   402.8 2044.71   441.6 2072.06   462.9 2089.51   473.1 2096.05
   487.8 2108.15   497.2 2113.99   512.7 2120.65   525.7 2128.68   534.8 2132.34
#Mann= 3 ,-1 , 0
       0      .1       0  206.45    .045       0  236.21      .1       0
Bank Sta=206.45,236.21
XS Rating Curve= 0 ,0
Exp/Cntr(USF)=0,0
Exp/Cntr=0.3,0.1

Type RM Length L Ch R = 1 ,4378    ,165.6,162.4,159.2
XS GIS Cut Line= 4
1966191.59090486 230700.969490291966162.50032335230599.917996597
1966119.62999269230439.1542566331965992.55008395230226.333686584
#Sta/Elev= 30
       0 2033.34      42 2014.38    60.5 2004.59   105.2 1976.63   118.5 1966.87
   135.4 1951.94   142.2 1944.09   145.6 1941.11  158.821931.533   167.3 1930.09
  184.561931.533   193.2 1932.74   206.8 1932.33   216.9 1934.99   239.6  1952.2
   271.5 1969.87   286.5 1976.93   305.6 1990.01   313.3 1994.04   341.2 2013.53
   351.5 2018.65     377 2038.93   393.8  2050.5   416.4 2067.63     447 2085.19
     456 2089.62   472.7 2102.47   487.1 2109.87   504.3 2122.13   519.4 2128.74
#Mann= 3 ,-1 , 0
       0      .1       0  158.82    .045       0  184.56      .1       0
#XS Ineff= 2 , 0
                          192.82         1934.98
Permanent Ineff=
       F       F
Bank Sta=158.82,184.56
XS Rating Curve= 0 ,0
Exp/Cntr(USF)=0,0
Exp/Cntr=0.3,0.1

Type RM Length L Ch R = 1 ,4215    ,131,133.3,135.1
XS GIS Cut Line= 4
1966361.54114425 230659.630242871966320.20189683230534.081417374
1966263.55181704230400.8771756891966162.50032335230184.994439164
#Sta/Elev= 30
       0  2009.3    24.6 2003.01    52.2 1994.52      73 1985.25    93.7 1973.21
   117.9 1960.58   155.1 1935.27  176.041926.112   192.3 1924.84  203.791926.115
   210.1 1928.53   227.9 1928.91   231.5 1929.35   235.2  1930.9   245.7 1939.23
     260 1947.59     285 1966.11   292.8 1970.44     332 1997.97   339.6 2003.93
   351.7  2010.6     372 2027.56   386.5 2036.06   393.6 2043.12   410.9 2056.25
   447.9 2081.41   462.2 2089.86   482.5 2098.42   494.8 2104.98   515.3 2114.42
#Mann= 3 ,-1 , 0
       0      .1       0  176.04    .045       0  203.79      .1       0
Bank Sta=176.04,203.79
XS Rating Curve= 0 ,0
Exp/Cntr(USF)=0,0
Exp/Cntr=0.3,0.1

Type RM Length L Ch R = 1 ,4082    ,208.2,201.8,194.7
XS GIS Cut Line= 4
1966477.73334996230604.5112463111966442.00807442230493.933012473
1966380.76474491230318.7090419291966271.88771467  230133.2778498
#Sta/Elev= 30
       0    2010    25.1 2005.62    49.4 1995.99    70.1 1986.03    90.3 1973.36
   101.1 1965.61   114.9 1957.53   134.4  1940.7   140.5 1936.27   152.4 1925.07
  159.921921.923   180.7 1920.81     191 1920.98  194.341921.923   198.3 1923.08
   212.2 1924.18     240 1924.97   247.7  1926.9   260.6 1935.82   278.2  1949.6
   313.8 1967.78   355.9 1992.48   390.5  2015.3   405.3 2026.36   423.5  2037.5
   443.2 2051.82   455.9 2058.59   475.3 2071.92   504.3 2084.88   516.9 2092.41
#Mann= 3 ,-1 , 0
       0      .1       0  159.92    .045       0  194.34      .1       0
Bank Sta=159.92,194.34
XS Rating Curve= 0 ,0
Exp/Cntr(USF)=0,0
Exp/Cntr=0.3,0.1

Type RM Length L Ch R = 1 ,3880    ,78.4,78.6,78.4
XS GIS Cut Line= 4
1966669.96935648230466.7137549121966586.61038021230357.836724672
1966487.94057155230213.2344188831966389.27076289230063.528502302
#Sta/Elev= 30
       0  1965.2    17.9 1959.57    42.6 1953.06    85.9 1943.28   101.2 1937.33
   129.4 1923.41   140.1 1921.15   151.8 1917.56   177.4 1915.72  185.071914.471
   197.2 1912.83  207.371914.471   213.1 1917.37     225  1926.7   244.9 1937.25
   256.5 1944.29   280.6 1954.45   328.1 1981.47     336 1985.38   351.3 1995.87
   362.5  2005.5   396.3 2032.39   418.5 2043.96   430.3 2052.71     446 2066.26
   453.9 2071.06   469.7 2078.18   475.8 2082.76   485.3 2091.39   491.5 2095.06
#Mann= 3 ,-1 , 0
       0      .1       0  185.07    .045       0  207.37      .1       0
Bank Sta=185.07,207.37
XS Rating Curve= 0 ,0
Exp/Cntr(USF)=0,0
Exp/Cntr=0.3,0.1

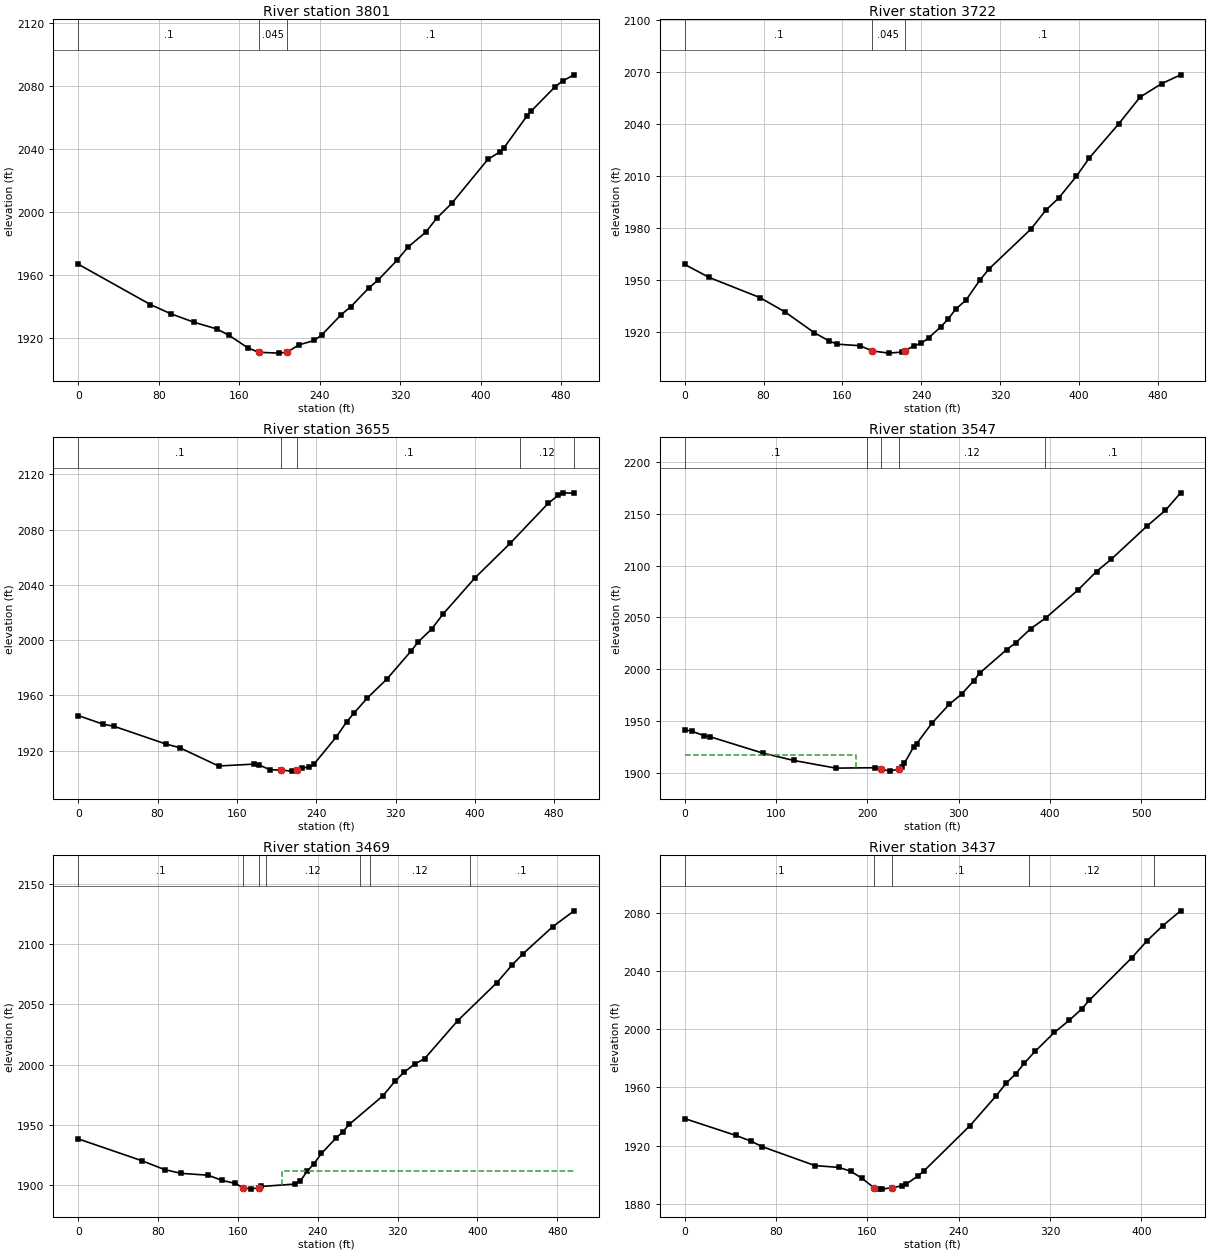
Type RM Length L Ch R = 1 ,3801    ,78.8,79,78.5
XS GIS Cut Line= 4
1966722.06739597230444.2053550191966657.44916522230330.302033011
1966564.35510396230182.4467592511966460.30880021 230026.92491574
#Sta/Elev= 30
       0 1966.83    71.8 1941.14    91.8 1935.35   114.9 1929.94   137.8 1925.61
   150.1 1921.54   168.5 1913.61   179.5 1910.79   199.3 1910.26   207.7 1910.87
   219.1 1915.48   234.6  1918.3   242.4 1922.05   261.4 1934.76     271 1939.83
   288.9 1951.79   297.9 1956.64     317 1969.42   327.9 1977.81   345.4 1987.17
   356.3 1996.09   371.5 2005.71     407 2033.44   418.9 2038.21   422.8 2040.53
   445.7 2060.92   450.4 2064.38   474.1  2079.8     482 2083.57   492.8 2087.26
#Mann= 3 ,-1 , 0
       0      .1       0   179.5    .045       0   207.7      .1       0
Bank Sta=179.5,207.7
XS Rating Curve= 0 ,0
Exp/Cntr(USF)=0,0
Exp/Cntr=0.3,0.1

Type RM Length L Ch R = 1 ,3722    ,65.4,67.4,69.6
XS GIS Cut Line= 4
1966790.75481191230419.0800541821966731.21268599230299.995802356
1966627.43926655230136.6802569951966545.78149386229980.169526024
#Sta/Elev= 30
       0  1959.1    24.9 1951.59    76.3 1939.99     102 1931.63   131.3  1919.8
   146.8 1914.86   154.8 1913.12   177.9 1912.23  190.081909.264   206.9 1907.96
   220.6  1908.6   223.31909.263   232.3 1912.09   240.1 1913.66   247.4 1916.73
   260.2  1923.3   267.3 1927.65     275 1933.33   285.5 1938.59   299.7 1950.27
   309.2 1956.76   351.5 1979.62   366.3 1990.36   379.4 1997.35   397.3 2009.89
   410.7 2020.63   440.2 2040.06     462 2055.61   483.9 2063.38   503.2 2068.48
#Mann= 3 ,-1 , 0
       0      .1       0  190.08    .045       0   223.3      .1       0
Bank Sta=190.08,223.3
XS Rating Curve= 0 ,0
Exp/Cntr(USF)=0,0
Exp/Cntr=0.3,0.1

Type RM Length L Ch R = 1 ,3655    ,98.2,107.6,115.1
XS GIS Cut Line= 4
1966826.11369973230391.6345910151966786.68562673230277.731269007
1966702.35335947230113.4476314961966626.78288622229933.830854484
#Sta/Elev= 30
       0 1945.35    25.2 1939.05    36.2 1937.57    88.3 1924.76   102.2  1922.1
   141.6 1908.83   177.1 1910.18   182.2  1909.7   193.3 1906.12   204.3 1905.89
   215.4 1905.11  220.95 1905.86   225.8 1907.43   233.2 1908.02   237.5 1909.92
     260 1929.63   270.7 1940.71   278.1  1947.1   291.6 1958.09   311.1 1971.62
     336 1992.29   343.1 1998.88   356.4 2007.94     368 2018.86     400 2044.92
   435.6 2070.03   474.1 2099.07   484.2 2104.83     489  2106.6   500.1 2106.31
#Mann= 5 ,-1 , 0
       0      .1       0   204.3    .045       0  220.95      .1       0
   445.2     .12       0  500.07      .1       0
Bank Sta=204.3,220.95
XS Rating Curve= 0 ,0
Exp/Cntr(USF)=0,0
Exp/Cntr=0.3,0.1

Type RM Length L Ch R = 1 ,3547    ,68.8,78.6,80.2
XS GIS Cut Line= 4
1966846.89453062230378.2511678421966840.08971623230228.545251261
1966836.68730904230073.7357238871966843.49212343229835.567220235
#Sta/Elev= 30
       0  1941.3     7.7 1940.02    20.9 1935.74    27.4  1934.7    85.5 1918.79
   119.4  1911.7   165.4 1904.29     208 1904.66   215.21903.276   224.4 1901.38
  234.321903.274   237.6 1905.63   240.3 1908.78   250.7 1924.76     254 1927.96
   270.4 1947.42   289.5 1965.83   303.2 1975.82   316.3  1988.5   322.9 1996.06
   352.4 2018.73   362.3 2025.34   378.7 2038.93   395.1 2049.32   430.7 2076.48
   450.9 2094.31   467.3 2106.39   506.7 2138.64   526.4 2153.46     543 2170.35
#Mann= 5 ,-1 , 0
       0      .1       0  199.86     .12       0   215.2    .045       0
  234.32     .12       0  394.71      .1       0
#XS Ineff= 2 , 0
          188.01 1916.61
Permanent Ineff=
       F       F
Bank Sta=215.2,234.32
XS Rating Curve= 0 ,0
Exp/Cntr(USF)=0,0
Exp/Cntr=0.3,0.1

Type RM Length L Ch R = 1 ,3469    ,36.7,32.3,37.1
XS GIS Cut Line= 4
1966863.81321199230368.4679914371966865.43569067230250.027047707
1966920.59996583230116.9837958471966938.44723133229883.346865751
#Sta/Elev= 30
       0 1938.18    63.6 1920.05    86.5 1912.64   102.9  1909.5   130.1 1907.95
   144.3 1903.59     157  1901.2     1651897.687   173.1 1896.37   180.7 1897.53
   183.4 1898.59     217 1900.58   222.4    1903   229.5 1911.38   235.9 1917.24
   243.7 1926.03   257.9 1938.58   264.9 1943.86   271.4 1950.14   305.4  1974.1
   317.5  1986.3   326.7 1993.83   337.2 2000.44   347.1 2004.99     380 2036.35
   419.4  2068.1   434.9 2083.04   445.8  2092.3   475.4 2114.71   496.8 2127.91
#Mann= 7 ,-1 , 0
       0      .1       0     165    .045       0   180.7      .1       0
  188.45     .12       0  282.48      .1       0  292.48     .12       0
  392.48      .1       0
#XS Ineff= 2 , 0
                           203.9         1911.56
Permanent Ineff=
       F       F
Bank Sta=165,180.7
XS Rating Curve= 0 ,0
Exp/Cntr(USF)=0,0
Exp/Cntr=0.3,0.1

Type RM Length L Ch R = 1 ,3437    ,47.3,41.7,39.3
XS GIS Cut Line= 4
1966885.96359678230378.8429128361966893.17690613 230275.31070809
1966935.18382526230154.806010764 1966986.2479142229958.386078102
#Sta/Elev= 30
       0 1938.49    44.5 1927.01    57.7 1923.13    67.5 1919.32   114.1 1906.22
     135 1904.97   145.4 1902.35   155.4 1897.39   165.7 1891.04   169.7 1890.12
   173.2 1890.06   181.1 1891.07   190.6 1892.31   194.1 1893.59   204.5 1899.21
   209.5 1902.57   249.8 1933.62   272.7 1954.12   281.8 1963.07   289.9 1969.15
   297.3 1976.49   306.8 1984.63   323.8 1997.73   336.8 2006.03   347.5 2013.67
   354.3 2019.72   391.6    2049   405.1 2060.77   418.7 2070.98   434.3 2081.18
#Mann= 5 ,-1 , 0
       0      .1       0   165.7    .045       0   181.1      .1       0
   301.4     .12       0   411.4      .1       0
Bank Sta=165.7,181.1
XS Rating Curve= 0 ,0
Exp/Cntr(USF)=0,0
Exp/Cntr=0.3,0.1

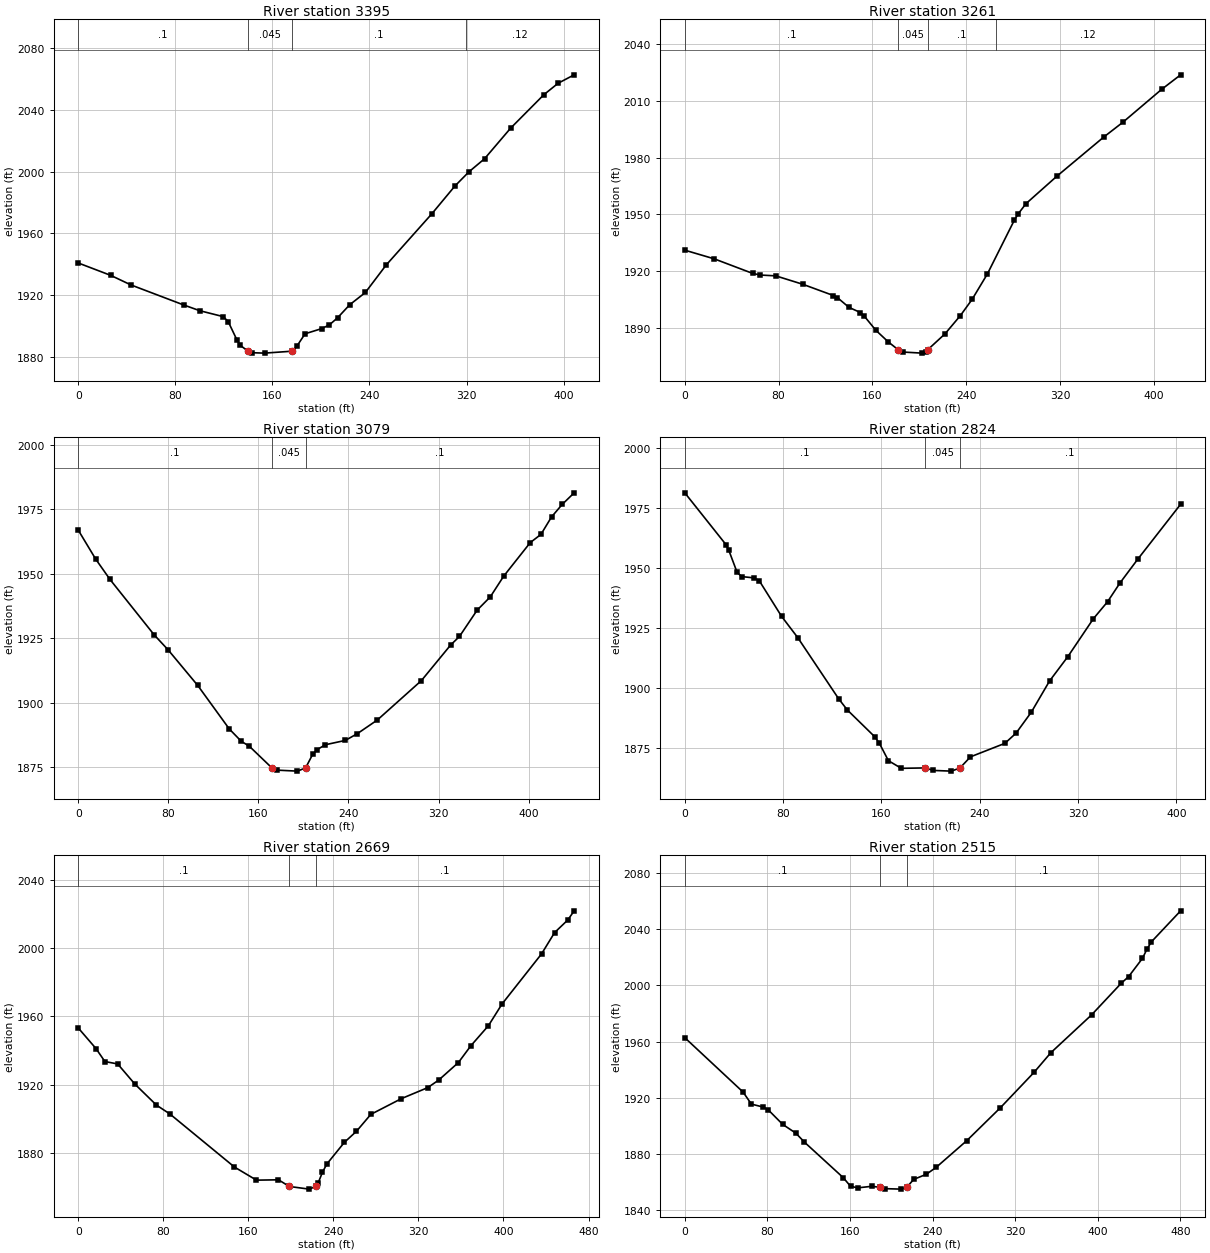
Type RM Length L Ch R = 1 ,3395    ,135.4,133.9,129.8
XS GIS Cut Line= 4
1966921.74748891230393.562000219 1966935.3571177230317.007838331
1966969.38118965230138.3814605931967011.91127958229995.480358402
#Sta/Elev= 30
       0 1940.79    26.7 1932.79    43.3 1926.63    86.7 1913.68   100.1 1909.92
   119.5 1906.07   123.5 1902.92   130.7 1891.05   133.5 1887.52  139.881883.691
   143.5 1882.72   153.5 1882.46  175.841883.691   176.9 1883.87   180.3 1887.16
   186.9 1894.99   200.9  1898.4     207 1900.79   213.7 1905.35   223.7 1913.77
   236.6 1921.71   253.7 1939.45   291.4 1972.65   310.4 1990.61     322 1999.83
   334.8 2008.25   356.3 2028.05   383.7 2049.71   395.5 2057.16   408.7  2062.6
#Mann= 4 ,-1 , 0
       0      .1       0  139.88    .045       0  175.84      .1       0
  319.59     .12       0
Bank Sta=139.88,175.84
XS Rating Curve= 0 ,0
Exp/Cntr(USF)=0,0
Exp/Cntr=0.3,0.1

Type RM Length L Ch R = 1 ,3261    ,192.3,181.5,173.6
XS GIS Cut Line= 4
 1967071.4534055230451.4029225351967073.15460909230345.928299489
1967076.55701629230179.2103469331967059.54498031230029.504430352
#Sta/Elev= 30
       0 1931.15    25.1 1926.58    57.9 1918.89    64.5 1918.03    77.6  1917.6
   100.6 1913.17   126.8 1907.22   130.1 1906.15     140    1901   149.8 1898.25
   153.1 1896.35   162.9 1888.93   173.5  1882.8  182.221878.524   185.9 1877.43
   202.3 1876.85   205.6 1877.58  207.011878.527     222 1887.06   235.1 1896.69
     245 1905.14   258.1 1918.63   281.1 1947.01   284.4 1950.33     291 1955.68
   317.4 1970.19   357.3 1990.79   373.6 1998.59   406.6 2015.91   422.9 2023.63
#Mann= 4 ,-1 , 0
       0      .1       0  182.22    .045       0  207.01      .1       0
  265.49     .12       0
Bank Sta=182.22,207.01
XS Rating Curve= 0 ,0
Exp/Cntr(USF)=0,0
Exp/Cntr=0.3,0.1

Type RM Length L Ch R = 1 ,3079    ,271.2,255.7,236.8
XS GIS Cut Line= 4
1967314.72551994230385.0559822321967280.70144799230286.386173576
1967197.34247171230087.3453526671967130.99553141229986.974340414
#Sta/Elev= 30
       0 1966.86    15.4 1955.69    28.1  1947.8    67.4 1926.28    79.7 1920.51
   106.1 1906.66   134.1  1889.8   144.8    1885   151.9  1883.1  171.991874.681
   176.8 1873.82   194.6 1873.44  201.921874.684   208.2 1879.97   212.3 1881.82
   219.5 1883.68   237.2 1885.35   247.9 1887.98   265.7 1893.29   304.8 1908.56
   330.7 1922.32   338.6 1925.67   354.3 1935.87     366 1941.03   377.9 1949.06
   401.5 1962.08     411 1965.26   420.4 1972.03   429.9  1976.9   440.5 1981.38
#Mann= 3 ,-1 , 0
       0      .1       0  171.99    .045       0  201.92      .1       0
Bank Sta=171.99,201.92
XS Rating Curve= 0 ,0
Exp/Cntr(USF)=0,0
Exp/Cntr=0.3,0.1

Type RM Length L Ch R = 1 ,2824    ,144.7,154.3,164.4
XS GIS Cut Line= 4
1967498.45550847230162.1983109581967406.59051421230063.528502302
1967306.21950195230014.1935979741967163.31839976229949.547861269
#Sta/Elev= 30
       0 1981.29    33.6 1959.63    35.8 1957.34    42.6 1948.08    46.3 1946.36
      56 1945.84    60.5 1944.71    78.8 1929.75    91.9 1920.93   125.2 1895.41
   132.2 1890.78   154.7 1879.51   158.4  1876.8   165.7 1869.59   176.2 1866.41
   195.8 1866.58   202.2 1865.53   216.9 1865.24  223.821866.508   232.5  1871.2
   260.5 1876.83   269.6 1881.09     282 1889.83   296.8  1902.8   311.7 1912.97
   332.5  1928.8     344 1935.84   354.1 1943.67   368.5 1953.54   403.5 1976.52
#Mann= 3 ,-1 , 0
       0      .1       0   195.8    .045       0  223.82      .1       0
Bank Sta=195.8,223.82
XS Rating Curve= 0 ,0
Exp/Cntr(USF)=0,0
Exp/Cntr=0.3,0.1

Type RM Length L Ch R = 1 ,2669    ,153.3,154.8,154
XS GIS Cut Line= 4
1967554.59522719 230078.83933468 1967476.3398617229971.663508036
1967396.38329262229867.890088588 1967273.8966336229706.275746825
#Sta/Elev= 30
       0  1953.2    16.6 1941.22      25 1933.62      37 1932.22    53.2 1920.43
    73.5 1908.13    86.1 1902.97   146.9  1871.9   167.6 1864.24   188.3 1864.44
  198.551860.542   217.2 1858.99  223.38 1860.54   225.6 1862.52   229.7 1868.91
   233.9 1873.75   250.4 1886.41   261.7 1892.84   275.2 1902.72     304 1911.94
   328.7 1918.35     339 1922.75   357.6 1933.04   369.4 1942.92   385.8 1954.56
   398.7 1967.34   435.8 1996.57   448.1 2009.06   460.5 2016.42   466.5 2021.78
#Mann= 3 ,-1 , 0
       0      .1       0  198.55    .045       0  223.38      .1       0
Bank Sta=198.55,223.38
XS Rating Curve= 0 ,0
Exp/Cntr(USF)=0,0
Exp/Cntr=0.3,0.1

Type RM Length L Ch R = 1 ,2515    ,206.2,202.3,195.9
XS GIS Cut Line= 4
 1967685.5879042229997.181561999 1967617.5397603229915.523789319
1967513.76634085229774.3238907251967379.37125665229628.020381339
#Sta/Elev= 30
       0 1962.72    56.4 1923.97    64.5 1915.35    76.1 1913.21    80.8 1911.26
    94.8 1900.89   107.6  1894.6   115.9  1888.2   153.4 1862.94   160.5 1856.77
   167.4 1855.62   180.9 1856.72     189 1856.06   193.5 1855.07   209.4 1854.72
  215.231856.199   221.6 1861.64   233.8 1865.27   243.4 1870.21   273.1  1889.3
   305.7 1912.81   338.2 1937.96   354.4 1951.92   393.9 1978.94   422.7 2001.55
   429.8 2006.26   443.2 2019.25   447.6 2025.84   451.9 2031.08   480.2 2053.19
#Mann= 3 ,-1 , 0
       0      .1       0     189    .045       0  215.23      .1       0
Bank Sta=189,215.23
XS Rating Curve= 0 ,0
Exp/Cntr(USF)=0,0
Exp/Cntr=0.3,0.1