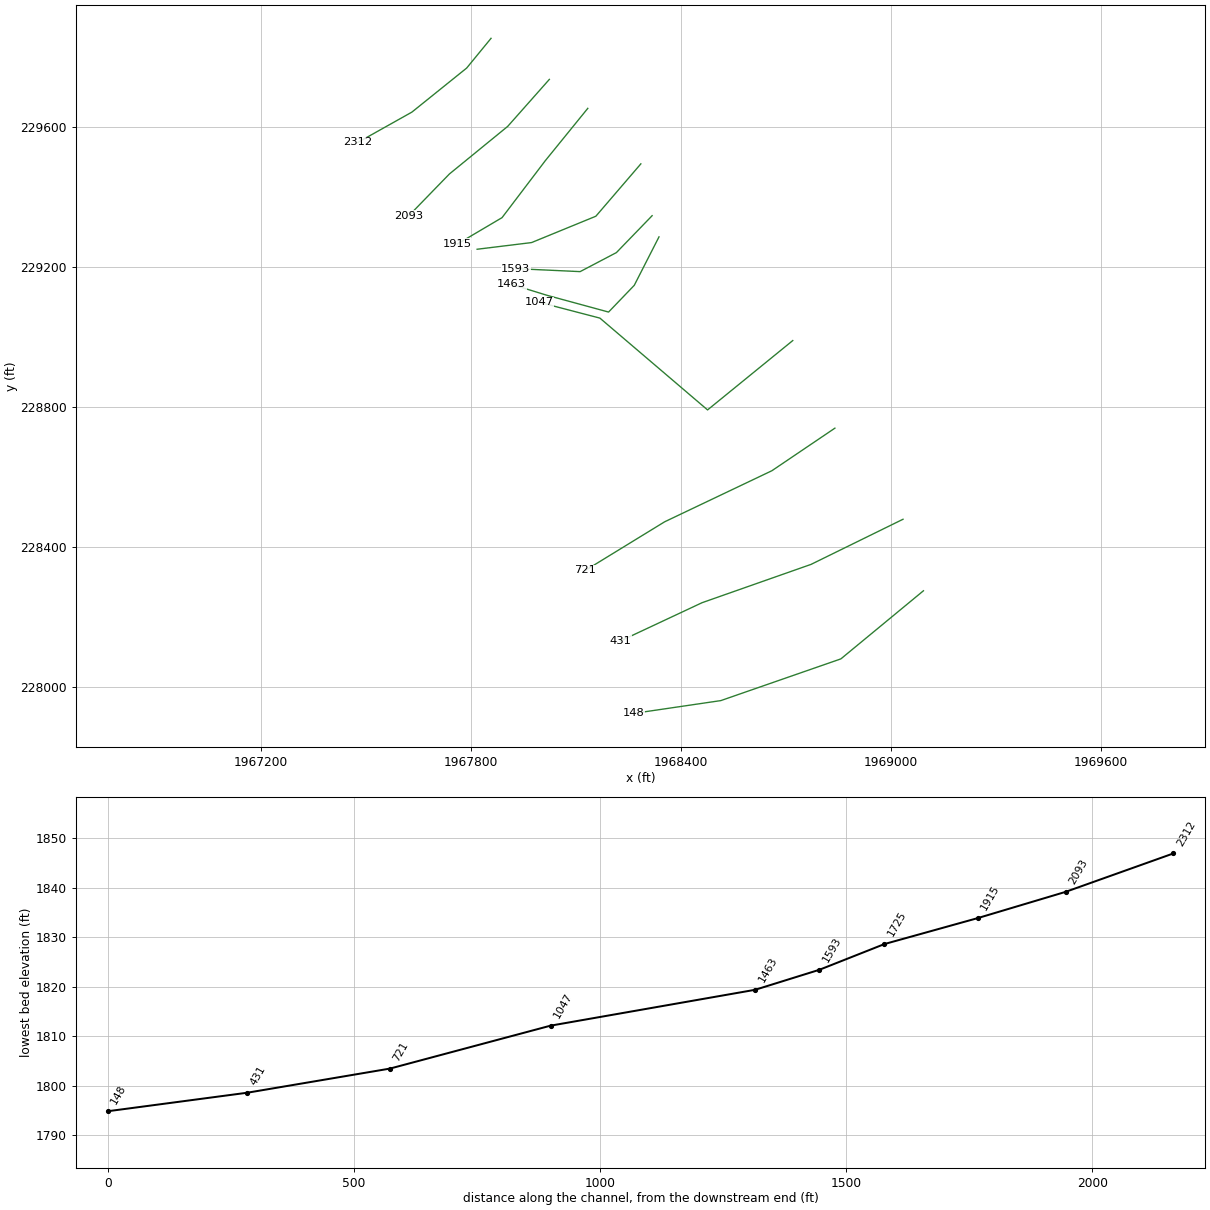
HEC-RAS study WHOAKBR.prj: WHOAKBR

--- WHOAKBR.g01 (geometry) --- (continued)

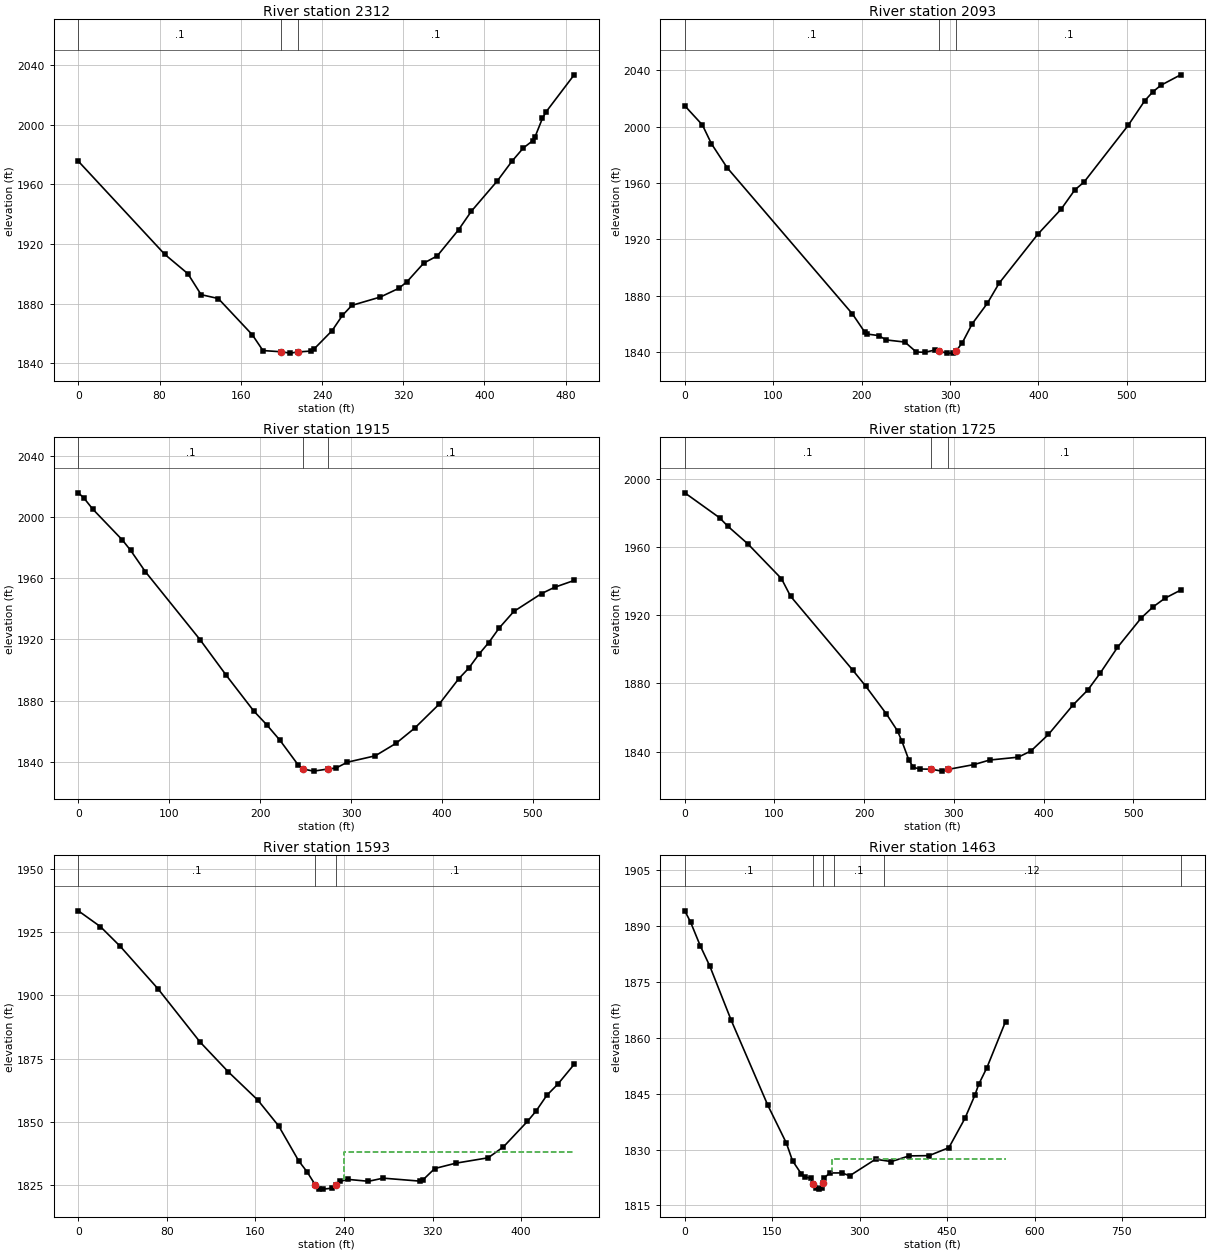
Type RM Length L Ch R = 1 ,2312    ,217.4,219.2,216.5
XS GIS Cut Line= 4
1967857.40946755229854.2804598081967787.66012005229769.220279932
1967631.14938908229643.331213717 1967476.3398617229556.569830243
#Sta/Elev= 30
       0 1975.42    85.1 1913.08   107.9 1900.09   120.9 1886.08   137.8 1883.49
   171.4 1859.16   181.8 1848.65   199.4 1847.85   208.7 1846.93     2161847.683
     229 1848.32   232.1 1849.66   249.9 1861.97   260.1 1872.22   269.4  1878.9
   297.4 1884.48   315.5 1890.28   323.5  1894.6   340.1 1907.15   353.5 1912.05
   374.4 1929.45     387 1941.88   412.7 1962.29     427 1975.37   438.3 1984.32
   447.4 1989.08   449.6 1991.42   457.1 2004.21   460.9 2008.69   488.3 2033.26
#Mann= 3 ,-1 , 0
       0      .1       0   199.4    .045       0     216      .1       0
Bank Sta=199.4,216
XS Rating Curve= 0 ,0
Exp/Cntr(USF)=0,0
Exp/Cntr=0.3,0.1

Type RM Length L Ch R = 1 ,2093    ,171.5,178.2,179.9
XS GIS Cut Line= 4
 1968024.1274201 229736.897411581967905.04316828229602.502327376
1967738.32521572229466.4060395751967622.64337109 229347.32178775
#Sta/Elev= 30
       0 2014.89    19.9 2001.28    30.1 1987.96    47.8 1970.97   189.6 1867.01
   203.5 1854.14   206.6 1852.69   219.3 1851.62   227.7 1848.54   248.9 1847.03
   261.8 1839.98   271.2 1839.72   282.8 1841.34     287 1840.46   296.8 1839.16
   303.6 1839.16  306.721840.514     314  1846.7   325.1 1860.03   342.1 1874.47
   355.5 1888.83   399.4 1923.73   425.7 1941.48   441.1 1955.11   451.6 1960.72
   501.5    2001   520.2 2018.47   529.2 2024.69   538.5 2029.47   560.8 2036.89
#Mann= 3 ,-1 , 0
       0      .1       0     287    .045       0  306.72      .1       0
Bank Sta=287,306.72
XS Rating Curve= 0 ,0
Exp/Cntr(USF)=0,0
Exp/Cntr=0.3,0.1

Type RM Length L Ch R = 1 ,1915    ,199.5,189.5,177.4
XS GIS Cut Line= 4
1968134.03376847229654.0685729881968012.48397929229504.391559856
1967888.92510267229341.6554784641967761.34805121229266.314700042
#Sta/Elev= 30
       0 2015.68     6.1 2012.29    15.8 2005.08    48.5 1984.82    57.6 1978.02
    73.7 1964.17   133.7 1919.86   162.8 1896.37   192.8 1873.24   207.2 1864.15
   221.7 1854.05   242.1 1837.66  247.271835.238   258.7 1833.87  274.311835.239
   283.5 1835.92   295.8 1839.69   326.6 1843.88   349.4 1852.04     370 1862.01
   396.8  1877.6   418.4 1894.25   429.4 1901.16   440.8  1910.4   451.4 1917.88
   462.8 1927.34   478.9 1938.16   509.4 1949.85   523.8 1953.97   545.3 1958.44
#Mann= 3 ,-1 , 0
       0      .1       0  247.27    .045       0  274.31      .1       0
Bank Sta=247.27,274.31
XS Rating Curve= 0 ,0
Exp/Cntr(USF)=0,0
Exp/Cntr=0.3,0.1

Type RM Length L Ch R = 1 ,1725    ,129.5,132.3,132.9
XS GIS Cut Line= 4
1968285.71986903229495.3506664451968157.13827386229345.673653313
1967973.30677451229270.332874891 1967817.6024991229251.246544358
#Sta/Elev= 30
       0 1991.62    38.7 1977.04      48 1972.05    70.3 1961.73   107.8 1941.34
   117.9 1931.09   187.1 1887.89   201.6  1878.5   224.9 1862.04   237.2 1852.18
   242.2 1846.02   249.7 1835.34   254.8 1830.84   262.3 1829.88   274.9 1829.74
   286.7 1828.63   293.8 1829.66   322.7 1832.49   339.9 1835.12   371.8  1836.8
     386 1840.43   405.5 1850.11   432.9 1867.36   449.5 1876.22   463.3  1886.1
   482.5 1901.12     509 1918.35   522.1 1924.78   535.4 1929.89   552.9 1934.62
#Mann= 3 ,-1 , 0
       0      .1       0   274.9    .045       0   293.8      .1       0
Bank Sta=274.9,293.8
XS Rating Curve= 0 ,0
Exp/Cntr(USF)=0,0
Exp/Cntr=0.3,0.1

Type RM Length L Ch R = 1 ,1593    ,123.4,130.5,137
XS GIS Cut Line= 4
1968317.98505967229347.1968968491968215.91284382229241.722273804
1968112.13942437229187.2837586831967928.40943584229195.789776671
#Sta/Elev= 30
       0 1933.47      20  1927.2    37.9 1919.41    71.9 1902.67     110 1881.57
   135.3 1869.88   162.1 1858.65     181 1848.39   199.1 1834.57   206.5 1830.35
  214.211824.985   217.6 1823.64   221.3 1823.43   228.8 1823.79  232.411824.988
   236.2 1826.47   243.6 1827.28   262.1 1826.53   275.4 1827.77   308.3  1826.6
   311.6 1827.21     322 1831.58   341.1  1833.7   370.2 1835.82     384 1840.13
   405.7 1850.22   413.4 1854.25   423.2 1860.52   433.1 1864.92   447.9 1872.77
#Mann= 3 ,-1 , 0
       0      .1       0  214.21    .045       0  232.41      .1       0
#XS Ineff= 2 , 0
                             240         1838.01
Permanent Ineff=
       F       F
Bank Sta=214.21,232.41
XS Rating Curve= 0 ,0
Exp/Cntr(USF)=0,0
Exp/Cntr=0.3,0.1

Type RM Length L Ch R = 1 ,1463    ,415.4,415.4,411.3
XS GIS Cut Line= 6
1968337.66687973   229286.6932481968266.90205628229148.090798875
1968193.48001611229071.6769511621968017.51641194229119.552165678
1967973.21097348229133.2479106831967915.84084188229150.574360073
#Sta/Elev= 30
       0 1894.11     9.8 1891.12    26.5 1884.73    42.9 1879.28    79.7 1864.69
   142.4 1841.92   174.3 1831.74   184.8 1827.01   199.9 1823.48   206.1 1822.63
   216.1 1822.35  220.761820.746   225.1  1819.7   229.8 1819.39   234.7 1819.77
     237 1821.05   239.4 1822.41   248.5 1823.73   269.4 1823.74     283 1822.98
   327.2 1827.41   354.4 1826.79   384.9 1828.31     419 1828.38   453.1 1830.52
   480.6 1838.38   497.7 1844.61   504.2 1847.51   518.3 1851.99   550.3 1864.39
#Mann= 6 ,-1 , 0
       0      .1       0  220.76    .045       0     237     .12       0
  255.62      .1       0  341.59     .12       0   850.7      .1       0
#XS Ineff= 2 , 0
                          253.16         1827.36
Permanent Ineff=
       F       F
Bank Sta=220.76,237
XS Rating Curve= 0 ,0
Exp/Cntr=0.3,0.1

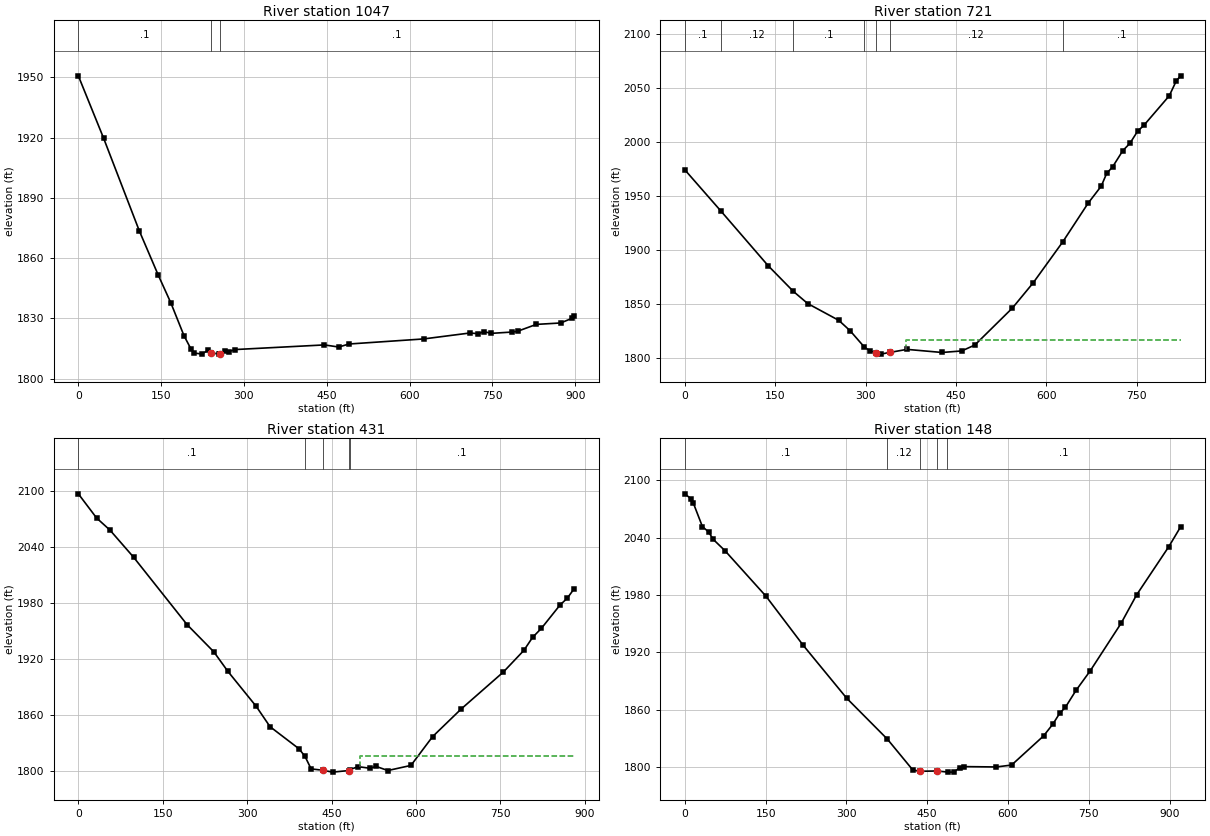
Type RM Length L Ch R = 1 ,1047    ,297.3,326.3,325.4
XS GIS Cut Line= 4
1968720.08770865228990.1530560531968476.49011038228791.875941185
1968168.68849397229054.3570742011967994.95997427229099.677557599
#Sta/Elev= 30
       0 1950.79    45.7 1919.78   110.5 1873.53   144.7 1851.56   167.7 1837.62
   191.4 1821.34   204.1 1814.68   209.3  1812.7   223.4 1812.22   235.7 1814.09
     2411812.877   254.3 1812.15   256.81812.192   265.7 1813.72     273 1813.45
   284.7 1814.44   445.8 1816.74   471.7 1815.69   490.3 1817.19   625.3 1819.71
   709.1 1822.67   724.5 1822.35   734.7 1823.35   748.2  1822.5   785.6 1823.15
   795.7 1823.54   829.6 1826.96   873.7 1827.67     894 1829.96   898.2 1831.03
#Mann= 3 ,-1 , 0
       0      .1       0     241    .045       0   256.8      .1       0
Bank Sta=241,256.8
XS Rating Curve= 0 ,0
Exp/Cntr(USF)=0,0
Exp/Cntr=0.3,0.1

Type RM Length L Ch R = 1 ,721     ,288.4,289.6,276.2
XS GIS Cut Line= 4
1968840.58948509228739.7336253541968660.45142428228618.018719403
1968353.72986129228471.9608322621968127.34013622228333.205839478
#Sta/Elev= 30
       0  1974.1      601935.862   138.1 1885.44     180 1861.61     204 1850.27
   255.5 1834.75   274.2 1825.19   297.41810.348   306.9 1806.51     317 1804.86
     325 1803.48  339.95 1805.02   368.6 1807.88   426.8 1805.01   459.5 1806.43
   481.3 1811.92   543.5  1846.1     578 1869.42  627.131907.379   669.2 1943.18
     691 1958.99     700 1970.78   709.8 1976.78   726.9 1991.91   738.5 1998.53
   751.4 2009.87   761.6 2015.16   803.8 2042.55   815.5 2056.39   822.7 2061.07
#Mann= 7 ,-1 , 0
       0      .1       0      60     .12       0     180      .1       0
   297.4     .12       0     317    .045       0  339.95     .12       0
  627.13      .1       0
#XS Ineff= 2 , 0
                          367.32         1816.61
Permanent Ineff=
       F       F
Bank Sta=317,339.95
XS Rating Curve= 0 ,0
Exp/Cntr=0.3,0.1

Type RM Length L Ch R = 1 ,431     ,283.7,283.5,283.2
XS GIS Cut Line= 4
1969035.33333461228479.2637266191968772.42913776228350.245926311
1968460.83897852228240.702510955 1968227.1463591228131.159095599
#Sta/Elev= 30
       0 2096.83    32.5 2070.91    56.2 2057.98    98.3 2028.84   193.3 1956.63
   240.8 1927.51   265.8 1906.57   316.3 1868.94   340.7 1847.31   392.3 1823.56
  402.861815.436   413.7 1802.09   434.6 1800.61     452 1798.61   480.6 1800.31
  482.861801.374   497.2 1804.48     518 1802.78   529.5 1804.68   550.1 1800.32
   591.1 1805.79   629.6 1836.64   680.3  1866.2   755.4 1905.89   791.9 1929.11
   807.3 1943.01   822.8 1952.56   856.5 1977.99   868.7 1984.77   881.2 1995.14
#Mann= 5 ,-1 , 0
       0      .1       0  402.86     .12       0   434.6    .045       0
   480.6     .12       0  482.86      .1       0
#XS Ineff= 2 , 0
                          500.75         1815.55
Permanent Ineff=
       F       F
Bank Sta=434.6,480.6
XS Rating Curve= 0 ,0
Exp/Cntr=0.3,0.1

Type RM Length L Ch R = 1 ,148     ,306.4,312.4,315.8
XS GIS Cut Line= 4
1969093.75648947228274.7826846211968857.62957193  228080.0388351
1968514.39353714227960.758227267  1968266.095129227924.243755482
#Sta/Elev= 30
       0 2085.87    11.4 2080.78    15.7 2076.39    32.7  2051.6    44.1 2046.09
    52.7 2038.28    74.4 2026.52   150.7 1978.82   219.8 1927.48   300.4 1872.23
  376.071829.338   423.2 1797.12   436.5 1795.78   468.4 1796.06   489.2 1794.87
   499.6 1794.91     510 1799.47   518.9 1800.64   578.2 1800.27   606.6 1802.26
   665.9 1832.68   683.1 1844.96   696.3 1856.72   706.3 1862.49   726.1 1880.25
   752.7 1900.87     810  1950.6   838.6 1980.11   898.6 2030.76   920.4 2051.37
#Mann= 5 ,-1 , 0
       0      .1       0  376.07     .12       0   436.5    .045       0
   468.4     .12       0  486.07      .1       0
Bank Sta=436.5,468.4
XS Rating Curve= 0 ,0
Exp/Cntr=0.3,0.1
LCMann Table=0

Chan Stop Cuts=-1
Use User Specified Reach Order=0
Composite Channel Slope=5